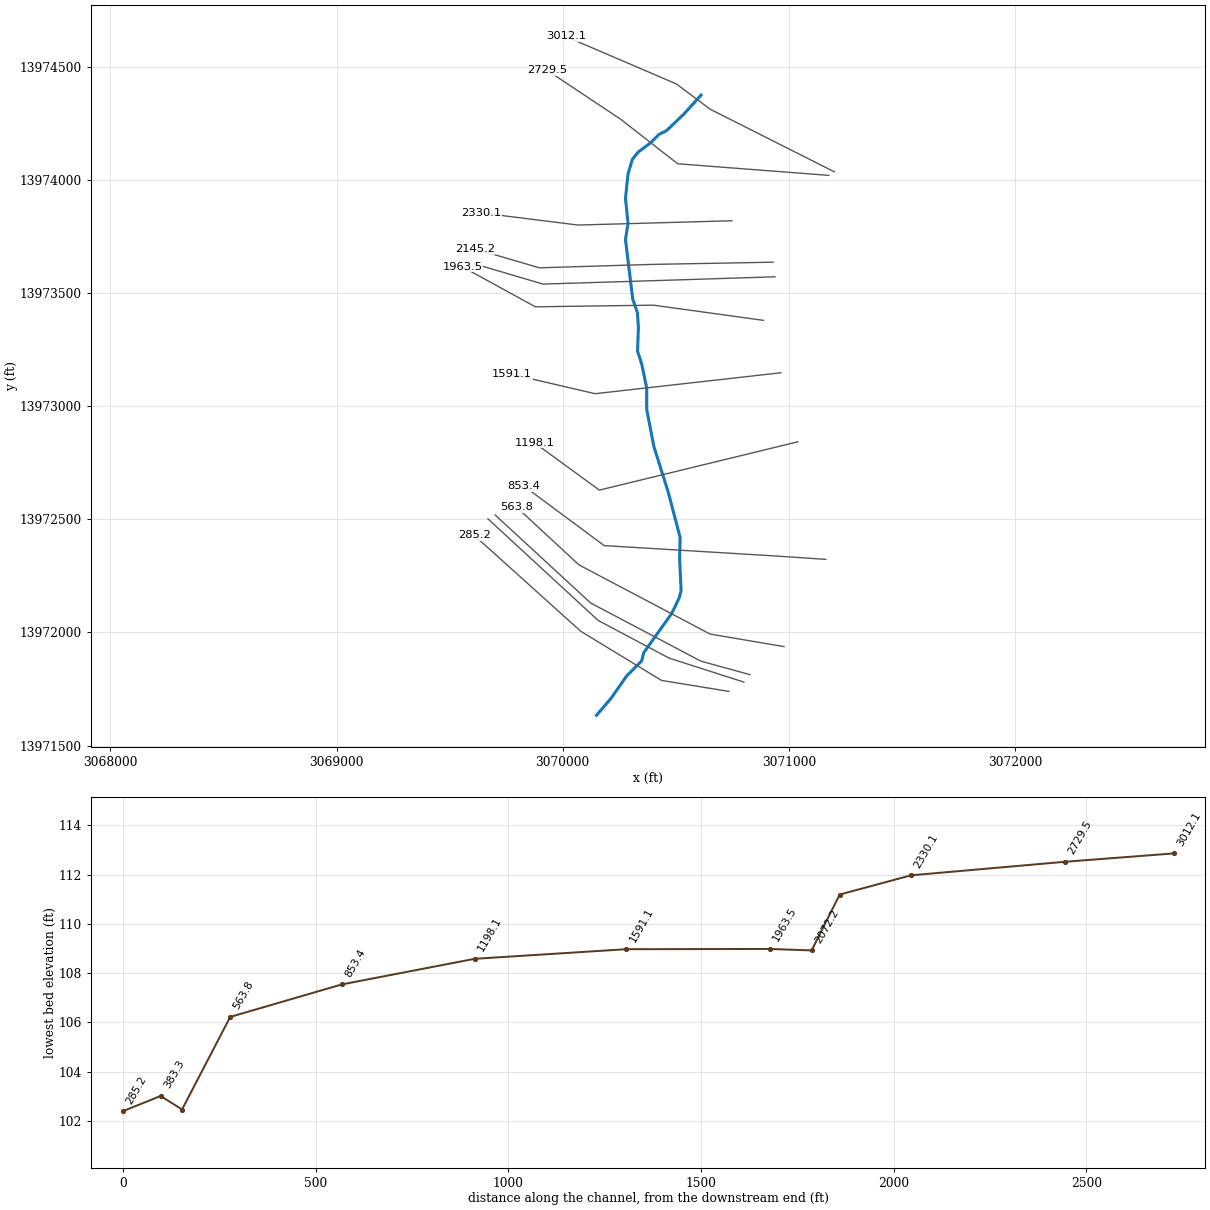
--- M102-00-00.PRJ (project) ---

Proj Title=M102-00-00
Current Plan=p03
Default Exp/Contr=.3,.1
English Units
Geom File=g01
Flow File=f02
Flow File=f03
Plan File=p02
Plan File=p03
Y Axis Title=Elevation
X Axis Title(PF)=Main Channel Distance
X Axis Title(XS)=Station
BEGIN DESCRIPTION:
Willow Creek
Tributary 1.77
HCFCD Unit M102-00-00
Flood Hazard Model
10, 2, 1, 0.2% Event
Filename M102-00-00.prj
Prepared by: Halff Associates, Inc Date: 03/05/2004
Reviewed by:                  Date:
STATUS Final RAS
END DESCRIPTION:
DSS Export Rating Curves= 0
DSS Export Rating Curve Sorted= 0
DSS Export Volume Flow Curves= 0
DXF OffsetX= 0
DXF OffsetY= 0
DXF ScaleX= 1
DXF ScaleY= 10

--- M102-00-00.p03 (plan) ---

Plan Title=Floodway
Program Version=3.11
Short Identifier=Floodway0607
Geom File=g01
Flow File=f03
Subcritical Flow
K Sum by GR= 0
Std Step Tol= 0.01
Critical Tol= 0.01
Num of Std Step Trials= 20
Max Error Tol= 0.3
Flow Tol Ratio= 0.001
Split Flow NTrial= 30
Split Flow Tol= 0.02
Split Flow Ratio= 0.02
Log Output Level= 0
Friction Slope Method= 1
Unsteady Friction Slope Method= 2
Unsteady Bridges Friction Slope Method= 1
Parabolic Critical Depth
Global Vel Dist= 0 , 0 , 0
Global Log Level= 0
CheckData=True
Encroach Param=-1 ,0,0, 2
Encroach River=M102-00-00
Encroach Reach=M102-00-00_0003
Encroach Node=3012.1
       1  4968.3  5033.6
Encroach Node=2729.5
       1  4971.2  5039.6
Encroach Node=2330.1
       1  4953.1  5046.9
Encroach Node=2145.2
       1    4965    5030
Encroach Node=2108.7
       1    4970    5025
Encroach Node=2072.2
       1    4980    5015
Encroach Node=1963.5
       1  4960.4    5043
Encroach Node=1591.1
       1  4972.6  5047.6
Encroach Node=1198.1
       1  4954.2  5034.5
Encroach Node=853.4
       1    4950    5038
Encroach Node=563.8
       1    4965    5040
Encroach Node=501.3
       1    4970    5035
Encroach Node=438.8
       1    4980    5025
Encroach Node=383.3
       1    4980    5025
Encroach Node=285.2
       1    4995    5040
Computation Interval=1HOUR
Output Interval=1HOUR
Run HTab= 0
Run UNet= 0
Run PostProcess= 0
UNET Theta= 1
UNET Theta Warmup= 1
UNET ZTol= 0.02
UNET ZSATol= 0.1
UNET MxIter= 20
UNET MaxInSteps= 20
UNET DtIC= 0
UNET DtMin= 0
UNET MaxCRTS= 20
UNET WFStab= 2
UNET SFStab= 1
UNET WFX= 1
UNET SFX= 1
UNET DSS MLevel= 4
UNET DZMax Abort= 100
UNET Convert EG Bridges=-1
UNET Use Existing IB Tables=-1
UNET Froude Reduction=False
UNET Froude Limit= 1
UNET Froude Power= 10
Instantaneous Interval=1HOUR
Write IC File= 0
Echo Input=False
Echo Output=False
Write Detailed= 0
Detailed Automatic Start=False, 10

--- M102-00-00.p02 (plan) ---

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Plan Title=FEMA Effective June 2007
Program Version=3.13
Short Identifier=FEMAeff0607
Geom File=g01
Flow File=f02
Encroach Param=-1 ,0,0, 0

--- M102-00-00.f03 (steady flow) ---

Flow Title=Floodway
Program Version=3.13
Number of Profiles= 2
Profile Names=1PCT_100yr,1PCTFloodway_100yrFW
River Rch & RM=M102-00-00,M102-00-00_0003       ,3012.1
    1030    1030
River Rch & RM=M102-00-00,M102-00-00_0003       ,1963.5
    1100    1100
River Rch & RM=M102-00-00,M102-00-00_0003       ,1591.1
    1140    1140
River Rch & RM=M102-00-00,M102-00-00_0003       ,853.4
    1200    1200
Boundary for River Rch & Prof#=M102-00-00,M102-00-00_0003       , 1
Up Type= 0
Dn Type= 3
Dn Slope=0.0038
Boundary for River Rch & Prof#=M102-00-00,M102-00-00_0003       , 2
Up Type= 0
Dn Type= 1
Dn Known WS=113.16
DSS Import GetInterval= 0
DSS Import GetPeak= 0
DSS Import FillOption= 0

--- M102-00-00.f02 (steady flow) ---

Flow Title=FEMA Effective June 2007
Program Version=3.13
Number of Profiles= 4
Profile Names=10PCT_10yr, 2PCT_50yr, 1PCT_100yr,0.2PCT_500yr
River Rch & RM=M102-00-00,M102-00-00_0003 ,3012.1
     490     850    1030    1570
River Rch & RM=M102-00-00,M102-00-00_0003 ,1963.5
     510     890    1100    1620
River Rch & RM=M102-00-00,M102-00-00_0003 ,1591.1
     530     920    1140    1660
River Rch & RM=M102-00-00,M102-00-00_0003 ,853.4
     550     950    1200    1700
Boundary for River Rch & Prof#=M102-00-00,M102-00-00_0003 , 1
Up Type= 0
Dn Type= 3
Dn Slope=0.0038
Boundary for River Rch & Prof#=M102-00-00,M102-00-00_0003 , 2
Up Type= 0
Dn Type= 3
Dn Slope=0.0038
Boundary for River Rch & Prof#=M102-00-00,M102-00-00_0003 , 3
Up Type= 0
Dn Type= 3
Dn Slope=0.0038
Boundary for River Rch & Prof#=M102-00-00,M102-00-00_0003 , 4
Up Type= 0
Dn Type= 3
Dn Slope=0.0038
DSS Import GetInterval= 0
DSS Import GetPeak= 0
DSS Import FillOption= 0

--- M102-00-00.g01 (geometry) ---

Geom Title=M102-00-00 June 2007
Program Version=3.13

River Reach=M102-00-00      ,M102-00-00_0003
Reach XY= 30
      3070611.99     13974376.67       3070535.6     13974292.47
      3070458.34     13974218.69      3070427.09     13974203.93
      3070389.59      13974166.5      3070334.21     13974124.94
      3070308.17     13974092.82      3070289.07     13974028.58
      3070277.79     13973920.08      3070289.07      13973810.7
      3070277.79     13973737.79       3070309.9     13973474.76
      3070330.74     13973413.13      3070334.91     13973349.31
      3070331.23     13973243.73      3070349.65     13973187.26
      3070371.74     13973080.46      3070371.74     13972985.94
      3070403.73      13972821.3      3070466.63     13972621.62
      3070519.58     13972420.23      3070517.35      13972324.6
      3070523.92     13972184.99      3070515.24     13972152.87
      3070482.79     13972084.84      3070358.99     13971911.56
      3070349.44     13971874.23      3070283.47     13971808.26
      3070214.89     13971710.17      3070149.79     13971633.78

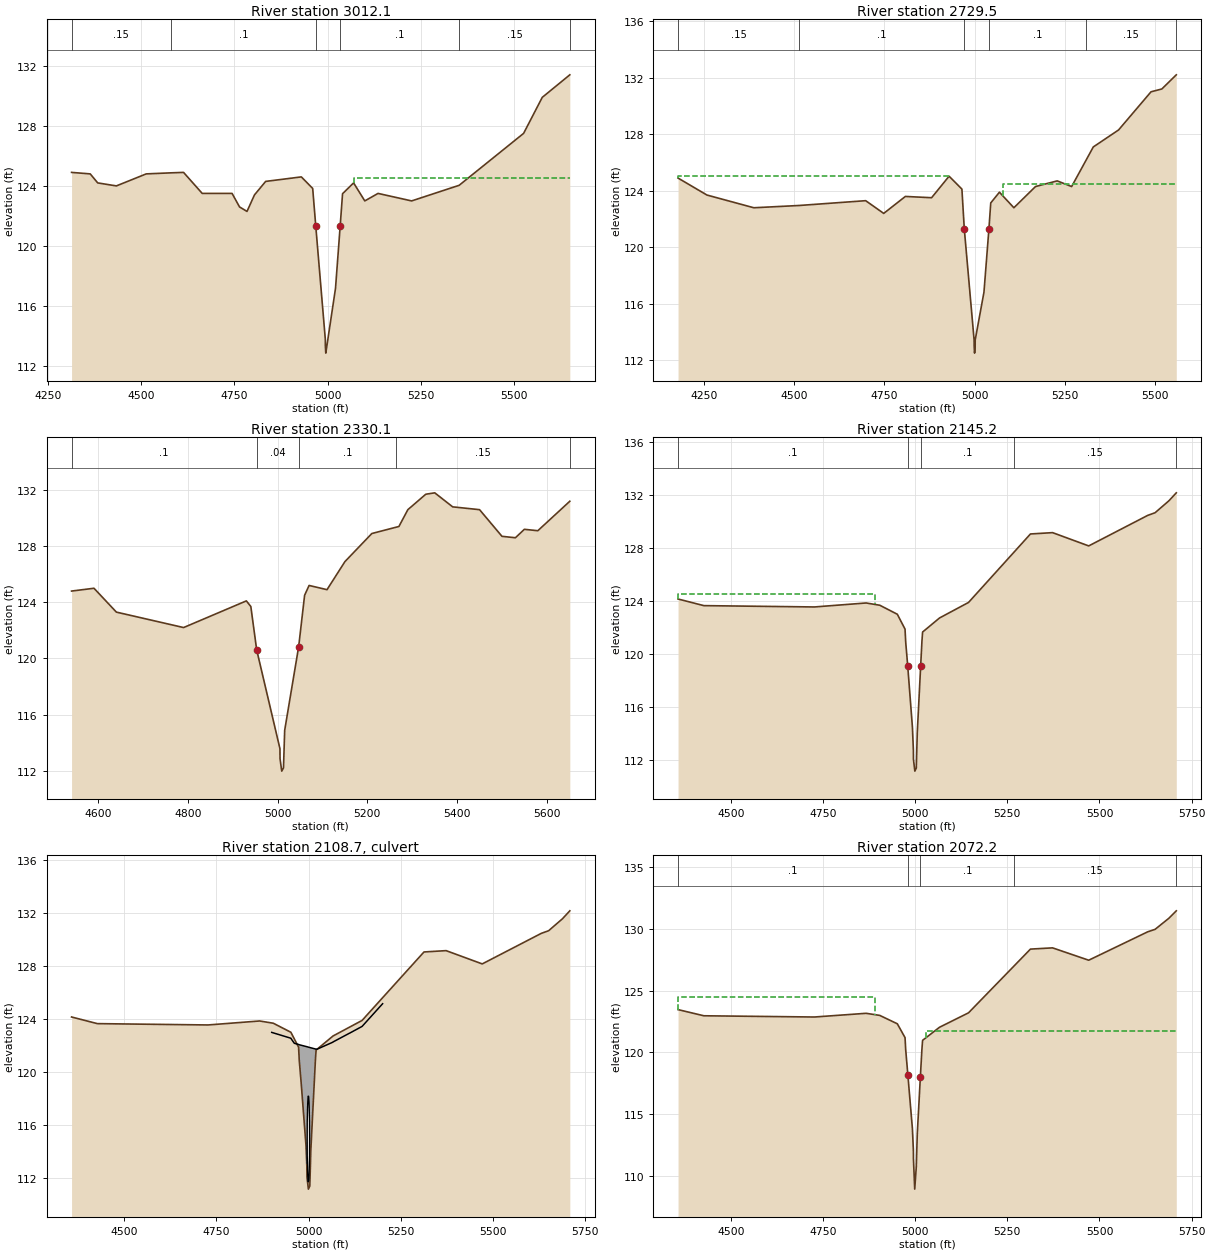
Type RM Length L Ch R = 1 ,3012.1  ,282.32,282.6,280.61
BEGIN DESCRIPTION:
Limits of Detailed Study
Cross Section 3012.1
Cross Section XS02.5
END DESCRIPTION:
XS GIS Cut Line= 4
      3071201.52      13974037.7      3070651.78      13974314.7
      3070503.45       13974426.      3070012.81      13974636.4
#Sta/Elev= 30
    4314   124.9    4364   124.8    4384   124.2    4434     124    4514   124.8
    4580  124.87    4614   124.9    4664   123.5    4744   123.5    4764   122.6
    4784   122.3    4804   123.4    4834   124.3  4929.6   124.6    4960  123.83
  4968.3   121.3  4993.8  113.79    4994  113.32  4995.1  112.86  5021.1  117.17
 5033.56   121.3    5040  123.48  5069.6   124.2  5099.6     123  5135.1   123.5
  5225.1     123  5352.4  124.04  5525.1   127.5  5575.1   129.9  5648.9   131.4
#Mann= 6 ,-1 , 0
    4314     .15       0    4580      .1       0  4968.3     .04       0
 5033.56      .1       0  5352.4     .15       0  5648.9      .2       0
#XS Ineff= 2 , 0
       0    4930   124.5    5070       0   124.5
Permanent Ineff=
       F       F
Bank Sta=4968.3,5033.56
Exp/Cntr=0.3,0.1

Type RM Length L Ch R = 1 ,2729.5  ,357.71,399.4,440.69
BEGIN DESCRIPTION:
Cross Section 2729.5
Cross Section XS02
END DESCRIPTION:
XS GIS Cut Line= 4
      3071177.42      13974021.8      3070508.71      13974073.2
      3070256.36      13974270.2      3069931.72      13974486.3
#Sta/Elev= 30
    4178   124.9    4258   123.7    4388   122.8  4513.6  122.96    4698   123.3
    4748   122.4    4808   123.6  4880.7  123.51  4929.1  125.03  4964.7  124.12
 4971.29   121.3  4998.5  113.45  4998.7  112.98  4999.8  112.52  5001.4  112.99
  5001.5  113.45  5025.8  116.83 5039.55   121.3  5044.6  123.14  5068.7   123.9
  5108.7   122.8  5168.7   124.3  5228.8   124.7  5268.8   124.3  5307.4   126.1
  5328.8   127.1  5398.8   128.3  5488.8     131  5518.8   131.2  5558.8   132.2
#Mann= 6 ,-1 , 0
    4178     .15       0  4513.6      .1       0 4971.29     .04       0
 5039.55      .1       0  5307.4     .15       0  5558.8      .2       0
#XS Ineff= 2 , 0
       0  4929.1  125.03    5078       0   124.5
Permanent Ineff=
       F       F
Bank Sta=4971.29,5039.55
Exp/Cntr=0.3,0.1

Type RM Length L Ch R = 1 ,2330.1  ,172.43,184.9,173.52
BEGIN DESCRIPTION:
Cross Section 2330.1
Cross Section XS01.7
END DESCRIPTION:
XS GIS Cut Line= 3
      3070748.62      13973821.1      3070068.46      13973802.1
      3069640.43      13973855.6
#Sta/Elev= 30
  4540.1   124.8  4590.1     125  4640.1   123.3  4790.1   122.2  4930.1   124.1
  4940.1   123.7 4953.15  120.61 5005.05  113.57 5005.25  112.86 5009.05  111.97
 5012.95   112.2 5015.65  114.88 5046.85  120.84  5060.1   124.5  5070.1   125.2
  5110.1   124.9  5150.1   126.9  5210.1   128.9  5264.2  129.35  5270.5   129.4
  5290.5   130.6  5330.5   131.7  5350.5   131.8  5390.5   130.8  5450.5   130.6
  5500.5   128.7  5530.5   128.6  5550.5   129.2  5580.5   129.1  5651.9   131.2
#Mann= 5 ,-1 , 0
  4540.1      .1       0 4953.15     .04       0 5046.85      .1       0
  5264.2     .15       0  5651.9      .2       0
#XS Ineff= 2 , 0
       0  4930.1   124.1               0
Permanent Ineff=
       F       F
Bank Sta=4953.15,5046.85
Exp/Cntr=0.5,0.3

Type RM Length L Ch R = 1 ,2145.2  ,73,73,73
BEGIN DESCRIPTION:
Upstream Section of Dover House Way Culvert
END DESCRIPTION:
XS GIS Cut Line= 4
      3070930.82      13973637.8      3070395.16      13973628.1
      3069897.46      13973612.9      3069611.84      13973696.4
#Sta/Elev= 28
  4357.2  124.16  4427.2  123.66  4727.2  123.56  4867.2  123.86  4904.3  123.69
  4951.9  123.01  4972.8  121.89  4974.6  120.91 4980.06  119.12  4992.8  114.51
  4995.4  112.79  4995.6  112.08  4999.4  111.19  5003.3  111.42    5006   114.1
 5015.18  119.12  5018.5  120.92  5020.4  121.67  5066.3  122.73    5145   123.9
  5269.3  127.72  5312.9  129.06  5372.9  129.16  5470.9  128.16  5630.9  130.46
  5650.9  130.66  5688.4  131.56  5708.4  132.16
#Mann= 5 ,-1 , 0
  4357.2      .1       0 4980.06     .04       0 5015.18      .1       0
  5269.3     .15       0  5708.4      .2       0
#XS Ineff= 2 , 0
       0    4890   124.5    5030       0  121.74
Permanent Ineff=
       F       F
Bank Sta=4980.06,5015.18
Exp/Cntr=0.5,0.3

Type RM Length L Ch R = 2 ,2108.7  ,,,
BEGIN DESCRIPTION:
DOVER HOUSE WAY
XS 2108.7
Structure ID: M102-00-00-02
END DESCRIPTION:
Bridge Culvert--1,0,-1,-1, 0
Deck Dist Width WeirC Skew NumUp NumDn MinLoCord MaxHiCord MaxSubmerge Is_Ogee
10,53,3,0, 24, 25, , , 0.95, 0, 1,1,,
    4900  4951.9  4952.7  4961.2  4972.8  4973.8  4974.6  4992.8  4995.4  4995.6
  4999.4  5003.3  5004.6    5006  5018.5  5019.2  5020.4  5023.3  5065.6  5066.3
  5110.2  5111.1    5145  5200.7
     123  122.56  122.52  122.18  122.09  122.08  122.07  121.94  121.92  121.92
  121.89  121.86  121.85  121.84  121.75  121.74  121.74  121.74  122.26  122.28
  122.93  122.94  123.45  125.16
                                                                                
                                                                                
                                
    4900  4951.9  4952.7  4961.2  4972.8  4973.8  4974.6  4992.8  4995.4  4995.6
  4999.4  5003.3  5004.6    5006  5018.5  5019.2  5020.4  5023.3  5065.6  5066.3
  5110.2  5111.1    5145  5200.7 5239.22
     123  122.56  122.52  122.18  122.09  122.08  122.07  121.94  121.92  121.92
  121.89  121.86  121.85  121.84  121.75  121.74  121.74  121.74  122.26  122.28
  122.93  122.94  123.45  125.16  126.09
                                                                                
                                                                                
                                        
BR Coef= 1 , 0 , 0 ,1.25, 0 ,,,0.8,-1,2,0,
WSPro=,,,, 1 ,,,, 0 ,,,, 0 ,,,,-1 ,-1 ,-1 , 0 , 0 , 0 , 0 , 0
Culvert=1,6.5,,53,0.015,0.5,1,1,3,111.72,4999.4,108.99,4999.4,Culvert #1  , 0 ,10
Culvert Bottom n=0.015
BC Design=,, 0 ,, 0 ,,,,,,
BC HTab HWMax=132.16

Type RM Length L Ch R = 1 ,2072.2  ,108.7,108.7,108.7
BEGIN DESCRIPTION:
Downstream Section of Dover House Way Culvert
END DESCRIPTION:
XS GIS Cut Line= 4
      3070939.13      13973573.2       3070420.8      13973556.7
      3069912.87       13973541.      3069606.44      13973631.5
#Sta/Elev= 28
  4357.2  123.46  4427.2  122.96  4727.2  122.86  4867.2  123.16  4904.3  122.99
  4951.9  122.31  4972.8  121.19  4974.6  120.21 4980.54  118.14  4992.8  113.81
  4995.4  112.09  4995.6  111.38 4999.05  108.92  5003.3  110.72    5006   113.4
 5014.34     118  5018.5  120.22  5020.4  120.97  5066.3  122.03    5145   123.2
  5269.3  127.02  5312.9  128.36  5372.9  128.46  5470.9  127.46  5630.9  129.76
  5650.9  129.96  5688.4  130.86  5708.4  131.46
#Mann= 5 ,-1 , 0
  4357.2      .1       0 4980.54     .04       0 5014.34      .1       0
  5269.3     .15       0  5708.4      .2       0
#XS Ineff= 2 , 0
       0    4890   124.5    5030       0  121.74
Permanent Ineff=
       F       F
Bank Sta=4980.54,5014.34
Exp/Cntr=0.5,0.3

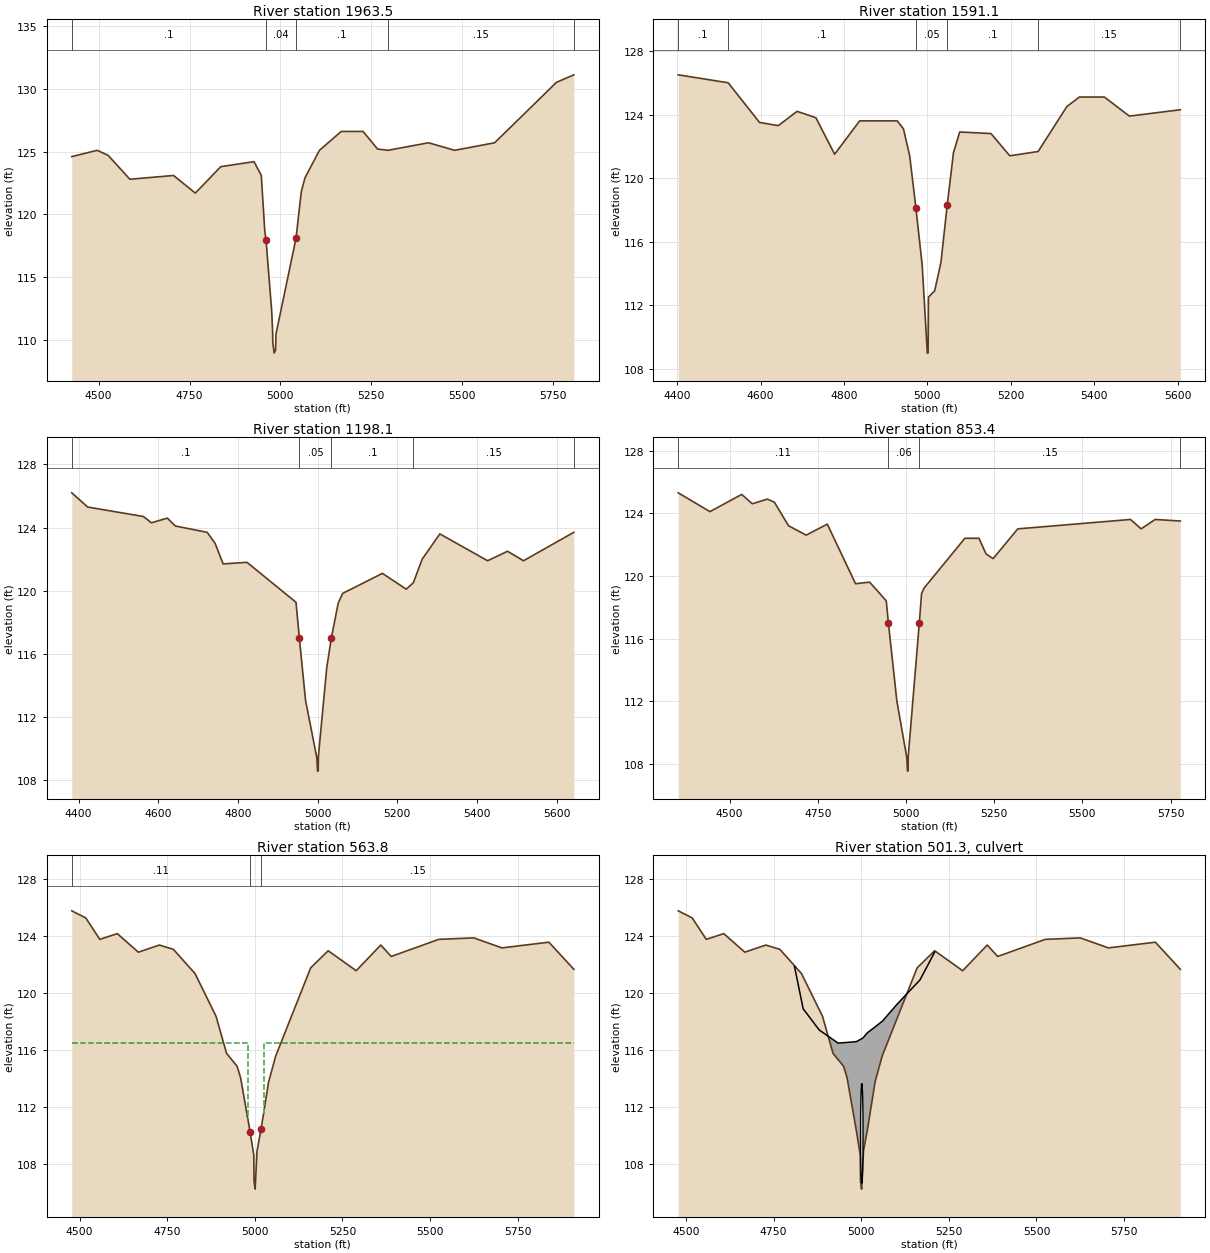
Type RM Length L Ch R = 1 ,1963.5  ,372,372.4,372
BEGIN DESCRIPTION:
Cross Section 1963.5
Cross Section XS01.5
END DESCRIPTION:
XS GIS Cut Line= 4
      3070888.11      13973380.6       3070401.2      13973447.8
      3069879.17      13973440.5      3069556.47      13973617.3
#Sta/Elev= 30
    4426   124.6    4496   125.1    4526   124.7    4586   122.8    4706   123.1
    4766   121.7    4836   123.8  4927.5   124.2  4947.5   123.1    4957  118.72
 4960.42     118  4976.2   112.3  4978.8  110.58    4979  109.87  4982.8  108.98
  4986.7  109.21    4988  110.51    5043   118.1  5057.5   121.8  5067.5   122.9
  5107.5   125.1  5167.5   126.6  5227.5   126.6  5267.5   125.2  5296.2   125.1
  5407.5   125.7  5479.6   125.1  5589.6   125.7  5759.6   130.5  5807.5   131.1
#Mann= 5 ,-1 , 0
    4426      .1       0 4960.42     .04       0    5043      .1       0
  5296.2     .15       0  5807.5      .2       0
Bank Sta=4960.42,5043
Exp/Cntr=0.3,0.1

Type RM Length L Ch R = 1 ,1591.1  ,387,393,400
BEGIN DESCRIPTION:
Cross Section 1591.1
END DESCRIPTION:
XS GIS Cut Line= 3
      3070965.12     13973148.72      3070143.56     13973056.21
       3069776.2     13973141.49
#Sta/Elev= 30
  4402.6   126.5  4522.3     126  4597.6   123.5  4642.6   123.3  4687.6   124.2
  4732.6   123.8  4777.6   121.5  4837.6   123.6  4927.6   123.6  4942.6   123.1
  4957.6   121.4  4972.6   118.1  4987.6   114.5  4999.9  108.97  5001.6  108.98
    5002   109.9  5002.6   112.5  5017.6   112.9  5032.6   114.7  5047.6   118.3
  5062.6   121.6  5077.6   122.9  5152.6   122.8  5197.6   121.4  5265.6  121.67
  5334.4   124.5  5364.4   125.1  5424.4   125.1  5484.4   123.9  5606.5   124.3
#Mann= 6 ,-1 , 0
  4402.6      .1       0  4522.3      .1       0  4972.6     .05       0
  5047.6      .1       0  5265.6     .15       0  5606.5      .2       0
Bank Sta=4972.6,5047.6
Exp/Cntr=0.3,0.1

Type RM Length L Ch R = 1 ,1198.1  ,362.71,344.7,326.75
BEGIN DESCRIPTION:
Cross Section 1198.1
Cross Section XS01
END DESCRIPTION:
XS GIS Cut Line= 3
      3071040.94      13972843.6      3070162.32      13972629.7
      3069874.21      13972839.8
#Sta/Elev= 30
  4382.7   126.2  4422.7   125.3  4562.7   124.7  4582.7   124.3  4622.7   124.6
  4642.7   124.1  4722.7   123.7  4742.7     123  4762.7   121.7  4822.7   121.8
  4945.8  119.27 4954.23     117  4969.7  113.07    4998  109.44  4999.9  108.58
  5001.6  108.59    5002  109.51    5023  115.13 5034.48     117  5051.7  119.21
  5062.9  119.83  5162.7   121.1  5222.7   120.1  5240.5  120.51  5262.7     122
    5307   123.6    5427   121.9    5477   122.5    5517   121.9  5643.5   123.7
#Mann= 5 ,-1 , 0
  4382.7      .1       0 4954.23     .05       0 5034.48      .1       0
  5240.5     .15       0  5643.5      .2       0
Bank Sta=4954.23,5034.48
Exp/Cntr=0.3,0.1

Type RM Length L Ch R = 1 ,853.4   ,258.6,289.6,207.35
BEGIN DESCRIPTION:
Cross Section 853.4
Cross Section XS0.7
END DESCRIPTION:
XS GIS Cut Line= 4
      3071164.06      13972323.4      3070931.91       13972339.
      3070183.69      13972384.3      3069829.25      13972647.1
#Sta/Elev= 30
  4354.2   125.3  4444.2   124.1  4534.2   125.2  4564.2   124.6  4606.9   124.9
  4626.9   124.7  4666.9   123.2  4716.9   122.6  4776.9   123.3  4856.9   119.5
  4896.9   119.6 4943.95  118.41 4950.05     117 4973.95  112.03 5002.25   108.4
 5004.15  107.54 5005.85  107.55 5006.25  108.47 5037.71     117 5044.15  118.88
 5051.55  119.23  5166.9   122.4  5206.9   122.4  5226.9   121.4  5246.9   121.1
  5316.9     123  5636.5   123.6  5666.5     123  5706.5   123.6  5777.7   123.5
#Mann= 4 ,-1 , 0
  4354.2     .11       0 4950.05     .06       0 5037.71     .15       0
  5777.7      .2       0
Bank Sta=4950.05,5037.71
Exp/Cntr=0.5,0.3

Type RM Length L Ch R = 1 ,563.8   ,125,125,125
BEGIN DESCRIPTION:
Upstream Section of Rayford Road Culvert
END DESCRIPTION:
XS GIS Cut Line= 4
      3070979.22      13971937.5      3070652.06       13971993.
      3070072.02       13972299.      3069797.58      13972553.2
#Sta/Elev= 30
  4477.7  125.74  4517.7  125.24  4557.7  123.74  4607.7  124.14  4667.7  122.84
  4727.7  123.34  4767.7  123.04  4829.5  121.34  4889.5  118.34  4919.5  115.74
  4949.5  114.84  4959.5  114.04  4986.5  110.26  4997.1  108.62    4998  106.75
    5001  106.22  5006.4  108.89  5018.1  110.45  5039.5  113.74  5059.5  115.54
  5159.5  121.74  5209.5  122.94  5289.5  121.54  5359.5  123.34  5389.5  122.54
  5525.3  123.74  5625.3  123.84  5705.3  123.14  5839.4  123.54  5910.6  121.64
#Mann= 3 ,-1 , 0
  4477.7     .11       0  4986.5     .06       0  5018.1     .15       0
#XS Ineff= 2 , 0
       0    4980  116.46    5025       0  116.46
Permanent Ineff=
       F       F
Bank Sta=4986.5,5018.1
Exp/Cntr=0.5,0.3

Type RM Length L Ch R = 2 ,501.3   ,,,
BEGIN DESCRIPTION:
W RAYFORD ROAD
XS 501.3
Structure ID: M102-00-00-01
END DESCRIPTION:
Bridge Culvert--1,0,-1,-1, 0
Deck Dist Width WeirC Skew NumUp NumDn MinLoCord MaxHiCord MaxSubmerge Is_Ogee
10,105,3,0, 28, 30, , , 0.95, 0, 1,1,,
  4809.5  4812.4  4834.2  4880.1  4902.4  4933.5    4934  4974.4  4986.5  4989.4
  4991.3  4997.1    4998  4998.5    5001  5001.9    5002  5004.8  5006.4  5015.9
  5018.1  5037.9  5061.3  5061.8  5103.8  5106.9  5167.5  5209.5
  121.84  121.49  118.87  117.38     117  116.47  116.46  116.54  116.57  116.61
  116.64  116.71  116.73  116.73  116.77  116.78  116.78  116.82  116.87  117.14
   117.2  117.57  118.02  118.04  119.23  119.31  120.89  122.84
                                                                                
                                                                                
                                                                
  4779.6  4809.5  4812.4  4834.2  4880.1  4902.4  4933.5    4934  4974.4  4986.5
  4989.4  4991.3  4997.1    4998  4998.5    5001  5001.9    5002  5004.8  5006.4
  5015.9  5018.1  5037.9  5061.3  5061.8  5103.8  5106.9  5167.5  5209.5  5239.5
  122.26  121.84  121.49  118.87  117.38     117  116.47  116.46  116.54  116.57
  116.61  116.64  116.71  116.73  116.73  116.77  116.78  116.78  116.82  116.87
  117.14   117.2  117.57  118.02  118.04  119.23  119.31  120.89  122.84  122.27
                                                                                
                                                                                
                                                                                
BR Coef= 1 , 0 , 0 ,1.25, 0 ,,,0.8,-1,2,0,
WSPro=,,,, 1 ,,,, 0 ,,,, 0 ,,,,-1 ,-1 ,-1 , 0 , 0 , 0 , 0 , 0
Culvert=1,7,,105,0.015,0.5,1,1,2,106.63,5001.6,103.01,5001.6,Culvert #1  , 0 ,10
Culvert Bottom n=0.015
BC Design=,, 0 ,, 0 ,,,,,,
BC HTab HWMax=125.74

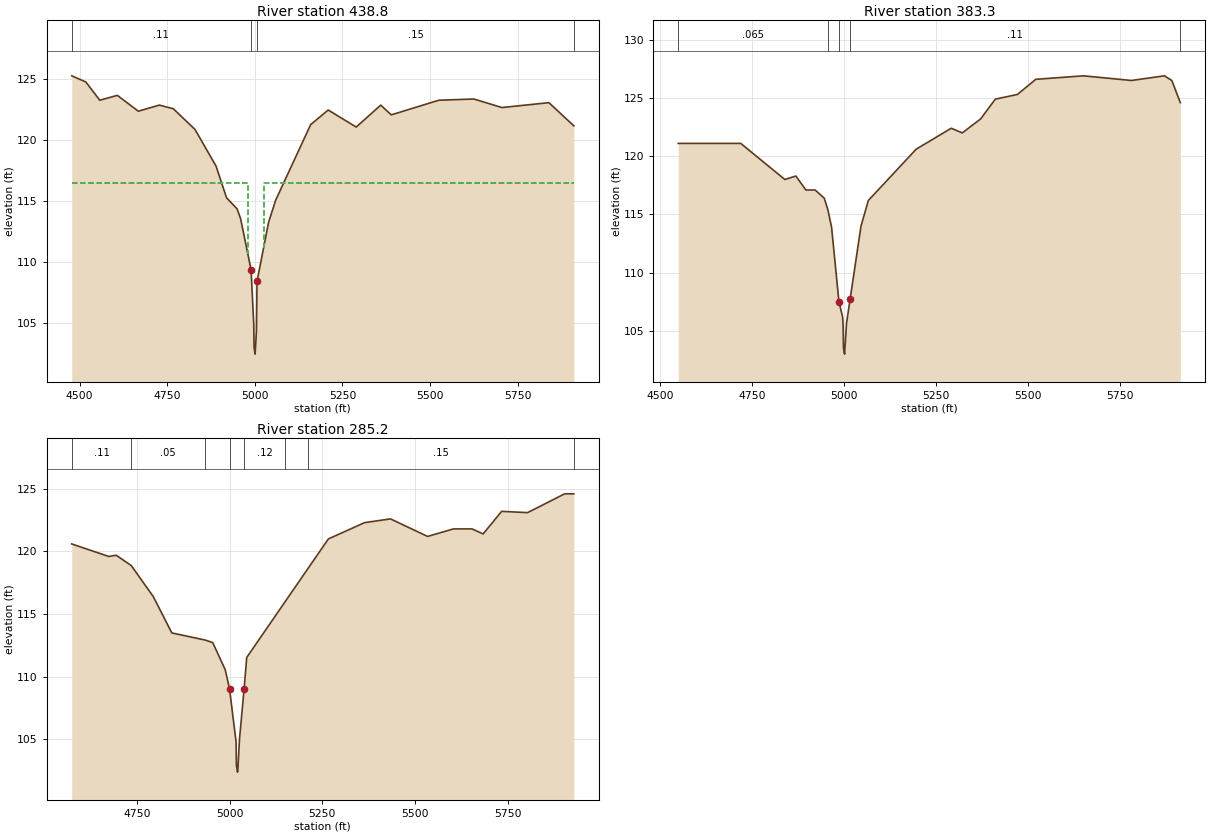
Type RM Length L Ch R = 1 ,438.8   ,55.5,55.5,55.5
BEGIN DESCRIPTION:
Downstream Section of Bridge/Culvert/Weir
END DESCRIPTION:
XS GIS Cut Line= 4
    3070828.7848    13971813.443    3070611.4304   13971873.1691
    3070123.7084    13972130.429    3069701.1628    13972520.017
#Sta/Elev= 30
  4477.7  125.27  4517.7  124.77  4557.7  123.27  4607.7  123.67  4667.7  122.37
  4727.7  122.87  4767.7  122.57  4829.5  120.87  4889.5  117.87  4919.5  115.27
  4949.5  114.37  4959.5  113.57  4989.5  109.37  4997.1  104.86    4998  102.99
    5001  102.46  5004.8  104.36  5006.4  108.42  5039.5  113.27  5059.5  115.07
  5159.5  121.27  5209.5  122.47  5289.5  121.07  5359.5  122.87  5389.5  122.07
  5525.3  123.27  5625.3  123.37  5705.3  122.67  5839.4  123.07  5910.6  121.17
#Mann= 4 ,-1 , 0
  4477.7     .11       0  4989.5     .06       0  5006.4     .15       0
  5910.6      .2       0
#XS Ineff= 2 , 0
       0    4980  116.46    5025       0  116.46
Permanent Ineff=
       F       F
Bank Sta=4989.5,5006.4
Exp/Cntr=0.5,0.3

Type RM Length L Ch R = 1 ,383.3   ,101.9,98.1,94.8
BEGIN DESCRIPTION:
Downstream of Rayford Road Culvert
END DESCRIPTION:
XS GIS Cut Line= 4
      3070801.55    13971780.529    3070471.0366   13971886.4947
    3070157.0939   13972053.1124      3069669.64      13972502.6
#Sta/Elev= 30
  4548.6   121.1  4718.6   121.1  4838.6     118  4868.6   118.3  4895.7   117.1
  4920.9   117.1  4945.7   116.4  4955.5  115.42  4965.7   113.9  4985.7   107.5
  4995.7   106.2  4997.1  105.41    4998  103.54    5001  103.01  5006.4  105.68
  5016.1  107.72  5045.7     114  5065.7   116.2  5195.7   120.6  5291.1   122.4
  5321.1     122  5371.1   123.2  5411.1   124.9  5471.1   125.3  5521.1   126.6
  5651.1   126.9  5781.1   126.5  5871.1   126.9  5891.1   126.5  5914.2   124.6
#Mann= 5 ,-1 , 0
  4548.6    .065       0  4955.5     .11       0  4985.7     .06       0
  5016.1     .11       0  5914.2      .2       0
Bank Sta=4985.7,5016.1
Exp/Cntr=0.3,0.1

Type RM Length L Ch R = 1 ,285.2   ,0,0,0
BEGIN DESCRIPTION:
Cross Section 285.2
Cross Section XS0.5
END DESCRIPTION:
XS GIS Cut Line= 4
      3070735.46      13971739.3       3070436.8      13971788.1
      3070080.04      13972005.3      3069608.24      13972430.1
#Sta/Elev= 30
  4573.7   120.6  4673.7   119.6  4693.7   119.7  4734.4  118.87  4793.7   116.4
  4843.7   113.5  4933.7  112.93  4954.1  112.73  4987.9  110.56  4999.5  109.04
  5017.2  104.79  5018.1  102.92  5021.1  102.39    5022   102.6  5026.5  105.06
  5038.8  109.01  5045.9  111.54  5150.2  116.02  5210.1  118.59  5266.3     121
    5364   122.3    5434   122.6    5534   121.2    5604   121.8    5654   121.8
    5684   121.4    5734   123.2    5804   123.1    5904   124.6  5928.8   124.6
#Mann= 8 ,-1 , 0
  4573.7     .11       0  4734.4     .05       0  4933.7     .12       0
  4999.5     .06       0  5038.8     .12       0  5150.2     .05       0
  5210.1     .15       0  5928.8      .2       0
Bank Sta=4999.5,5038.8
Exp/Cntr=0.3,0.1

Chan Stop Cuts=-1
Use User Specified Reach Order=0
User Specified Reach Order=M102-00-00      ,Reach - 1